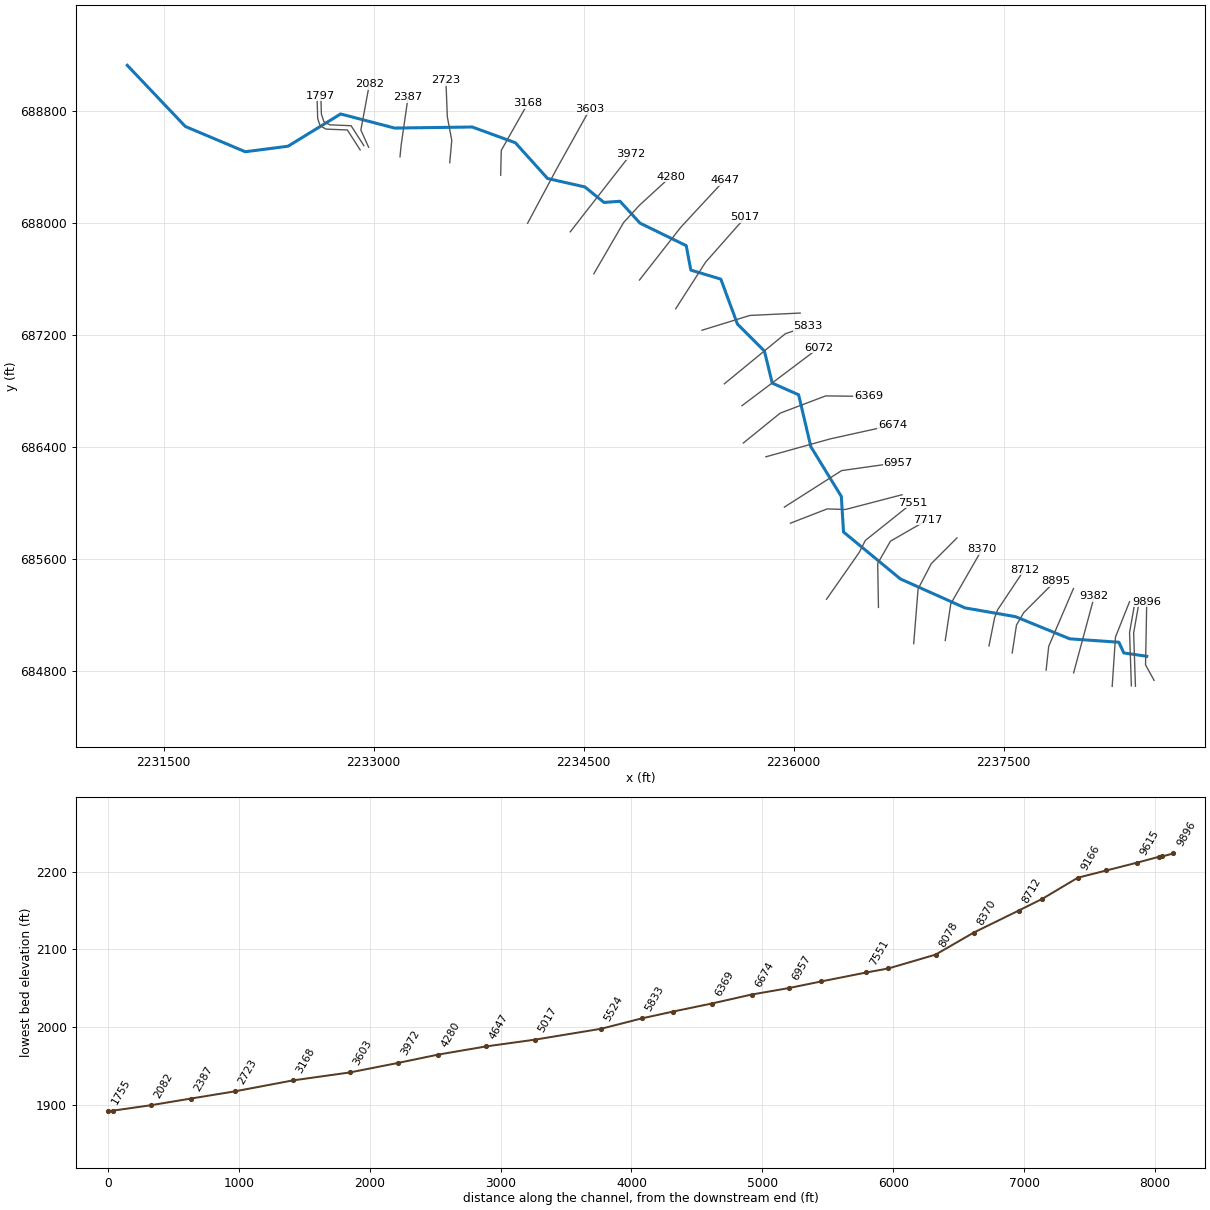
--- KETTLERN.prj (project) ---

Proj Title=KETTLERN
Current Plan=p01
Default Exp/Contr=0,0
English Units
Geom File=g01
Flow File=f01
Plan File=p01
BEGIN DESCRIPTION:
----------MODEL BY WOOD PLC 2022----------
AFH study
Randolph County, WV
HEC-RAS Version: RAS 6.2
Vertical Datum: NAVD88
Projection: NAD 1983 StatePlane West Virginia S FIPS 4702 (US Feet)
Terrain: 1-meter LIDAR (FEMA Region III 3DEP collected 2016-2018)
Land Use: 2019 NLCD
Hydrologic Method:
WV SIR2010-5033 regression equations
Additional Model Notes:
None
END DESCRIPTION:
DSS Export Rating Curves= 0
DSS Export Rating Curve Sorted= 0
DSS Export Volume Flow Curves= 0
DXF OffsetX= 0
DXF OffsetY= 0
DXF ScaleX= 0
DXF ScaleY= 0

--- KETTLERN.p01 (plan) ---

Plan Title=Floodplain
Program Version=6.20
Short Identifier=Floodplain
Geom File=g01
Flow File=f01
Subcritical Flow
K Sum by GR= 0
Std Step Tol= 0.01
Critical Tol= 0.01
Num of Std Step Trials= 20
Max Error Tol= 0.3
Flow Tol Ratio= 0.001
Split Flow NTrial= 30
Split Flow Tol= 0.02
Split Flow Ratio= 0.02
Log Output Level= 0
Friction Slope Method= 1
Unsteady Friction Slope Method= 2
Unsteady Bridges Friction Slope Method= 1
Parabolic Critical Depth
Global Vel Dist= 0 , 0 , 0
Global Log Level= 0
CheckData=True
Encroach Param=-1 ,0,0, 0
Mapping Interval=1HOUR
Computation Time Step Use Courant=        0
Computation Time Step Use Time Series=    0
Computation Time Step Count To Double=0
Computation Time Step Max Doubling=0
Computation Time Step Max Halving=0
Computation Time Step Residence Courant=0
Run HTab= 0
Run UNet= 0
Run Sediment= 0
Run PostProcess= 0
Run WQNet= 0
Run RASMapper=-1
UNET Theta= 0
UNET Theta Warmup= 0
UNET ZTol= 0
UNET ZSATol= 0
UNET MxIter= 0
UNET Max Iter WO Improvement= 0
UNET MaxInSteps= 0
UNET DtIC= 0
UNET DtMin= 0
UNET MaxCRTS= 0
UNET WFStab= 0
UNET SFStab= 0
UNET WFX= 1
UNET SFX= 1
UNET Gravity=32.174
UNET 1D Methodology=Finite Difference
UNET DSS MLevel= 1
UNET Pardiso=0
UNET DZMax Abort= 0
UNET Use Existing IB Tables= 0
UNET Froude Reduction=False
UNET Froude Limit= 0
UNET Froude Power= 0
UNET D1 Cores= 0
UNET WindReference=Eulerian
UNET WindDragFormulation=Hsu (1988)
UNET D2 Coriolis=0
UNET D2 Cores= 0
UNET D2 Theta= 1
UNET D2 Theta Warmup= 1
UNET D2 Z Tol= 0.01
UNET D2 Volume Tol= 0.01
UNET D2 Max Iterations= 20
UNET D2 Equation= 0
UNET D2 RampUpFraction=0.1
UNET D2 TimeSlices= 1
UNET D2 Turbulence Formulation=Non-Conservative (original)
UNET D2 Eddy Viscosity=0.3
UNET D2 Transverse Eddy Viscosity=0.1
UNET D2 Smagorinsky Mixing=0
UNET D2 BCVolumeCheck=0
UNET D2 Cores=0
UNET D2 SolverType=PARDISO (Direct)
UNET D2 Minimum Iterations= 2147483647
UNET D2 Maximum Iterations= 2147483647
UNET D2 Restart Number= 10
UNET D2 Relaxation Coeff=1.3
UNET D2 SOR Precondition Iterations= 10
UNET D2 ILUT Maximum Fill= 8
UNET D2 ILUT Tolerance=1E-08
UNET D1D2 MaxIter= 0
UNET D1D2 ZTol=0.01
UNET D1D2 QTol=0.1
UNET D1D2 MinQTol=1
Write IC File= 0
Write IC File at Fixed DateTime=0
Write IC File at Sim End=0
Echo Input=False
Echo Parameters=False
Echo Output=False
Write Detailed= 0
HDF Write Warmup=0
HDF Write Time Slices=0
HDF Flush=0
HDF Compression= 1
HDF Chunk Size= 1
HDF Spatial Parts= 1
HDF Use Max Rows=0
HDF Fixed Rows= 1
Calibration Method= 0
Calibration Iterations= 20
Calibration Max Change=0.05
Calibration Tolerance=0.2
Calibration Maximum=1.5
Calibration Minimum=0.5
Calibration Optimization Method= 1
WQ AD Non Conservative
WQ ULTIMATE=-1
WQ Max Comp Step=1HOUR
WQ Output Interval=15MIN
WQ Output Selected Increments= 0
WQ Output face flow=0
WQ Output face velocity=0
WQ Output face area=0
WQ Output face dispersion=0
WQ Output cell volume=0
WQ Output cell surface area=0
WQ Output cell continuity=0
WQ Output cumulative cell continuity=0
WQ Output face conc=0
WQ Output face dconc_dx=0
WQ Output face courant=0
WQ Output face peclet=0
WQ Output face adv mass=0
WQ Output face disp mass=0
WQ Output cell mass=0
WQ Output cell source sink temp=0
WQ Output nsm pathways=0
WQ Output nsm derived pathways=0
WQ Create Restart=0
WQ Fixed Restart=0
WQ System Summary=0
WQ Write To DSS=0
Sorting and Armoring Iterations= 10
XS Update Threshold= 0.02
Bed Roughness Predictor= 0
Hydraulics Update Threshold= 0.02
Energy Slope Method= 1
Volume Change Method= 1
Sediment Retention Method= 0
Sediment TS Multiplier= 1
Warm Up Method= 0
XS Weighting Method= 0
Number of US Weighted Cross Sections= 1
Number of DS Weighted Cross Sections= 1
Upstream XS Weight=0
Main XS Weight=1
Downstream XS Weight=0
Number of DS XS's Weighted with US Boundary= 1
Upstream Boundary Weight= 1
Weight of XSs Associated with US Boundary= 0
Number of US XS's Weighted with DS Boundary= 1
Downstream Boundary Weight= 0.5
Weight of XSs Associated with DS Boundary= 0.5
Percentile Method= 0
Sediment Output Level= 3
Mass or Volume Output= 0
Output Increment Type= 1
Profile and TS Output Increment= 1
Transport Output Increment 1
XS Output Flag= 0
XS Output Increment= 10
Read HDF5 Sediment Hotstart= 0
Sediment Hotstart Type= 0
Write Gradation File= 0
Read Gradation Hotstart= 0
Write HDF5 File= 1
Write Binary Output= 1
Write DSS Sediment File= 0
DSS Sediment Output Type= 1
SV Curve= 0
Specific Gage Flag= 0
Subcell Erosion Methods= 0
Subcell Deposition Methods= 0
Advection Scheme= 1
Matrix Solver= 0
Implicit Weighting Factor= 1
Maximum Outer Loop Convergence Iterations= 5
Convergence Maximum Absolute= 0.001
Convergence RMSE= 0.0001
Grain Fractions Max Abs Error= 0.001
Max Subgrid Regions= 1
Max Subgrid Length Scale= 3.402823E+38
Initial Layer Thickness= 3.402823E+38
Min Layer Thickness= 3.402823E+38
Max Layer Thickness= 3.402823E+38
Number of Layers= 5

--- KETTLERN.f01 (steady flow) ---

Flow Title=Flow
Program Version=6.20
Number of Profiles= 1
Profile Names=P100yr
River Rch & RM=KETTLERN,Main,9896
     469
River Rch & RM=KETTLERN,Main,5017
     525
River Rch & RM=KETTLERN,Main,3168
     605
Boundary for River Rch & Prof#=KETTLERN,Main            , 1
Up Type= 0
Dn Type= 3
Dn Slope=0.02164
DSS Import GetInterval= 0
DSS Import GetPeak= 0
DSS Import FillOption= 0

--- KETTLERN.g01 (geometry) ---

Geom Title=Geometry
Program Version=6.20

River Reach=KETTLERN        ,Main
Reach XY= 30
 2238522.3931933684902.3915573092238358.34863096684925.870995578
2238323.38579636 685002.411255092237973.06500003      685026.669
2237585.04400001685185.0890000162237224.15000002685247.806000009
2236763.23400003685454.2730000172236356.63700001685789.689999998
2236341.01199999686043.8560000212236123.30400003686399.065000013
2236035.80400001686769.8980000022235847.60900003686853.231000006
2235791.70600003687082.3980000022235598.65100002687275.453999996
     2235480.248687595.9400000132235266.18600003687660.349000022
2235233.02600001687835.0020000042234902.81800003687995.940000013
     2234760.456688151.8429999952234645.89600003688143.741999999
2234509.15600003688254.4070000052234242.66000001 688314.74000001
2234012.59700003688570.0230000022233705.23199999      688682.353
2233150.70700003688674.8649999952232764.83399999688775.448000014
2232389.16400002688545.1510000082232083.86300001688505.652999997
     2231655.612688686.1800000222231240.84212218689123.051753372

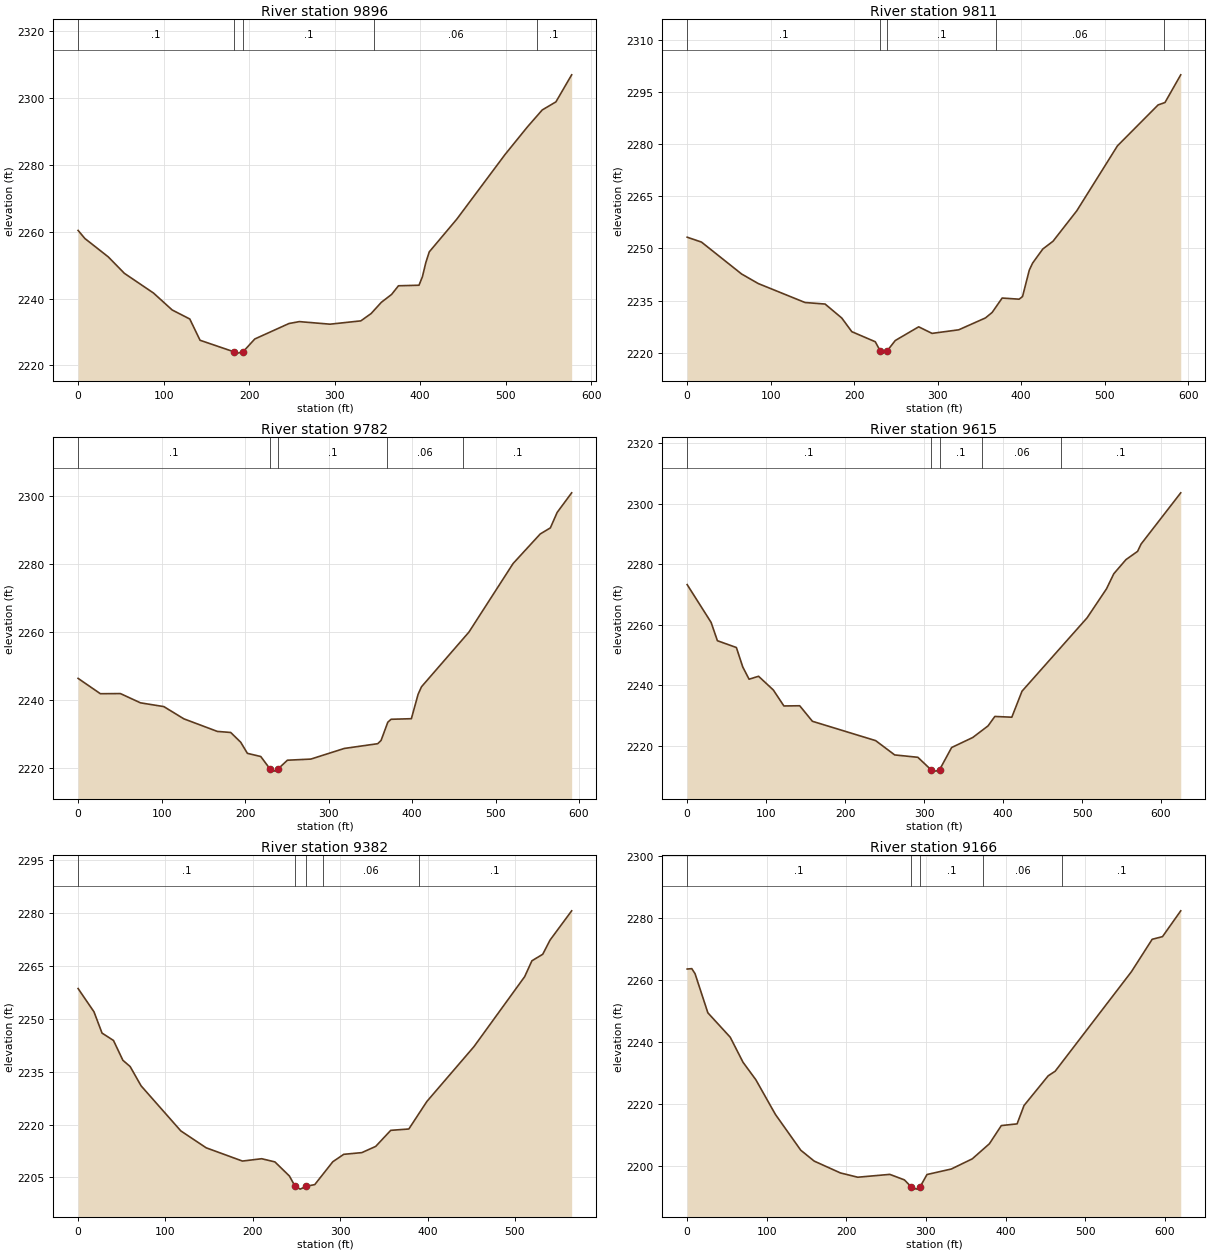
Type RM Length L Ch R = 1 ,9896    ,84.5,84.3,84.2
XS GIS Cut Line= 3
2238574.74022884684730.2681101572238513.79150367684840.826262786
2238522.29597695685291.563346581
#Sta/Elev= 30
       0 2260.41     7.9    2258    35.3 2252.49    54.1 2247.58    88.2 2241.67
     110 2236.61   130.6 2233.91   142.6 2227.55  181.872224.126   186.6  2223.7
  192.952224.126   206.6 2227.93   246.6 2232.56   258.7 2233.13   294.6 2232.36
   330.6 2233.35   342.6 2235.54   354.6 2238.91   366.6 2241.27   374.6 2243.85
   398.6 2244.01   402.6 2246.56   406.6  2250.8   410.6 2253.99   442.7 2263.75
   499.3 2283.15   525.5 2291.42   542.7 2296.45   558.7 2298.87   577.1 2306.96
#Mann= 5 ,-1,0
       0      .1       0  181.87    .045       0  192.95      .1       0
  346.25     .06       0  536.25      .1       0
Bank Sta=181.87,192.95
XS Rating Curve= 0 ,0
Exp/Cntr(USF)=0,0
Exp/Cntr=0.3,0.1

Type RM Length L Ch R = 1 ,9811    ,29.2,29.2,29.3
XS GIS Cut Line= 3
2238441.65616274684688.0431202332238428.81451649685069.341231854
2238465.36381734685275.795390737
#Sta/Elev= 30
       0 2253.24    17.1 2251.84    65.2 2242.64    85.2 2239.88   141.2 2234.42
   165.2 2233.98   185.2 2229.95   197.2 2226.02   225.3 2223.12  231.312220.457
   233.3 2219.84  239.412220.459   249.3 2223.48   277.3 2227.42   293.3 2225.53
   325.3 2226.56   357.3 2229.98   365.3 2231.56   377.3 2235.71   397.6 2235.38
   401.7 2236.14   409.8 2243.75   413.8 2245.79     426 2249.84   438.2 2252.07
   466.7 2260.85   515.4 2279.56   564.1 2291.35   572.3 2292.04   591.2 2300.02
#Mann= 5 ,-1,0
       0      .1       0  231.31    .045       0  239.41      .1       0
     370     .06       0  571.51      .1       0
Bank Sta=231.31,239.41
XS Rating Curve= 0 ,0
Exp/Cntr(USF)=0,0
Exp/Cntr=0.3,0.1

Type RM Length L Ch R = 1 ,9782    ,166.2,166.9,166.2
XS GIS Cut Line= 3
2238412.51550395684690.512667588 2238399.6738577685071.810779209
2238436.22315855685278.264938092
#Sta/Elev= 30
       0  2246.5    26.7 2241.99    50.7 2242.03    74.7 2239.31   102.7  2238.2
   126.7  2234.6   166.8  2230.9   182.8 2230.59   194.8 2227.72   202.8 2224.45
   218.8 2223.52  229.972219.836   234.8 2219.22  239.432219.838   250.7 2222.43
   278.8 2222.76   318.8 2225.89   358.9 2227.29   362.9 2228.24     371 2233.62
   374.9 2234.47   399.2 2234.64   407.3 2241.84   411.3 2244.02   468.2 2260.13
     521 2280.27   553.5 2288.97   565.7 2290.77   573.8  2295.3   591.2 2301.08
#Mann= 5 ,-1,0
       0      .1       0  229.97    .045       0  239.43      .1       0
     370     .06       0  461.51      .1       0
Bank Sta=229.97,239.43
XS Rating Curve= 0 ,0
Exp/Cntr(USF)=0,0
Exp/Cntr=0.3,0.1

Type RM Length L Ch R = 1 ,9615    ,234,232.9,231.7
XS GIS Cut Line= 3
 2238275.5803872684686.9732897672238299.02529249685039.341938739
2238399.52007526685291.940874566
#Sta/Elev= 30
       0 2273.27    30.3  2260.8    38.3 2254.74    62.3  2252.5    70.4 2246.07
    78.4 2242.03    90.4    2243   109.1 2238.47   122.5 2233.19   142.5 2233.26
   158.6 2228.13   238.7 2221.74   262.8 2217.02   292.1 2216.24  308.852212.114
   314.9 2211.67  319.582212.114   334.9 2219.47   361.6 2222.77     381 2226.61
   389.6 2229.73   411.1 2229.48     424 2238.07   506.4  2262.3     531 2271.88
   540.2 2276.85   555.6 2281.52   570.4 2284.27   574.7 2286.64     625 2303.59
#Mann= 5 ,-1,0
       0      .1       0  308.85    .045       0  319.58      .1       0
  373.15     .06       0  473.15      .1       0
Bank Sta=308.85,319.58
XS Rating Curve= 0 ,0
Exp/Cntr=0.3,0.1

Type RM Length L Ch R = 1 ,9382    ,217,216.7,215.8
XS GIS Cut Line= 2
2238000.11746776684783.6078303982238147.19273246685329.103401715
#Sta/Elev= 30
       0 2258.56    18.2 2251.96    27.4 2245.93    40.5 2243.84    51.3 2238.21
    59.6 2236.44    72.1 2230.98   117.6 2218.19   146.6  2213.4   188.1 2209.64
   210.2  2210.3   225.3  2209.4   241.9  2205.4  248.382202.491   254.3 2201.68
  261.182202.493   270.9 2202.96   291.6 2209.45   304.1 2211.55   324.8 2212.03
   340.7  2213.8   357.9 2218.35   378.6 2218.73   399.3 2226.55   453.2  2242.1
   511.2 2261.93   519.5 2266.43   531.9 2268.28   540.2 2272.28     565  2280.6
#Mann= 5 ,-1,0
       0      .1       0  248.38    .045       0  261.18      .1       0
     280     .06       0     390      .1       0
Bank Sta=248.38,261.18
XS Rating Curve= 0 ,0
Exp/Cntr(USF)=0,0
Exp/Cntr=0.3,0.1

Type RM Length L Ch R = 1 ,9166    ,270.9,270.8,269
XS GIS Cut Line= 3
2237803.65125596684803.364209238 2237822.3100582684973.488582587
2237999.01989116685386.177385032
#Sta/Elev= 30
       0 2263.59     5.8 2263.71     9.9 2262.09      26 2249.43    54.1 2241.54
    70.2 2233.43    86.3 2227.78   110.9 2216.56   142.7 2205.01   159.6 2201.48
   192.6 2197.65   214.3 2196.27   254.6 2197.19   272.9 2195.41  281.54 2193.15
   288.1 2192.42   292.6 2193.15   301.3 2197.14   331.8 2198.92   358.2 2202.21
   379.7 2207.09   394.7 2212.97   414.5 2213.52   423.2 2219.45   453.6 2229.07
   462.3 2230.53   558.1 2262.71   584.2  2273.2   597.2 2274.07   620.1 2282.41
#Mann= 5 ,-1,0
       0      .1       0  281.54    .045       0   292.6      .1       0
  371.14     .06       0  471.14      .1       0
Bank Sta=281.54,292.6
XS Rating Curve= 0 ,0
Exp/Cntr(USF)=0,0
Exp/Cntr=0.3,0.1

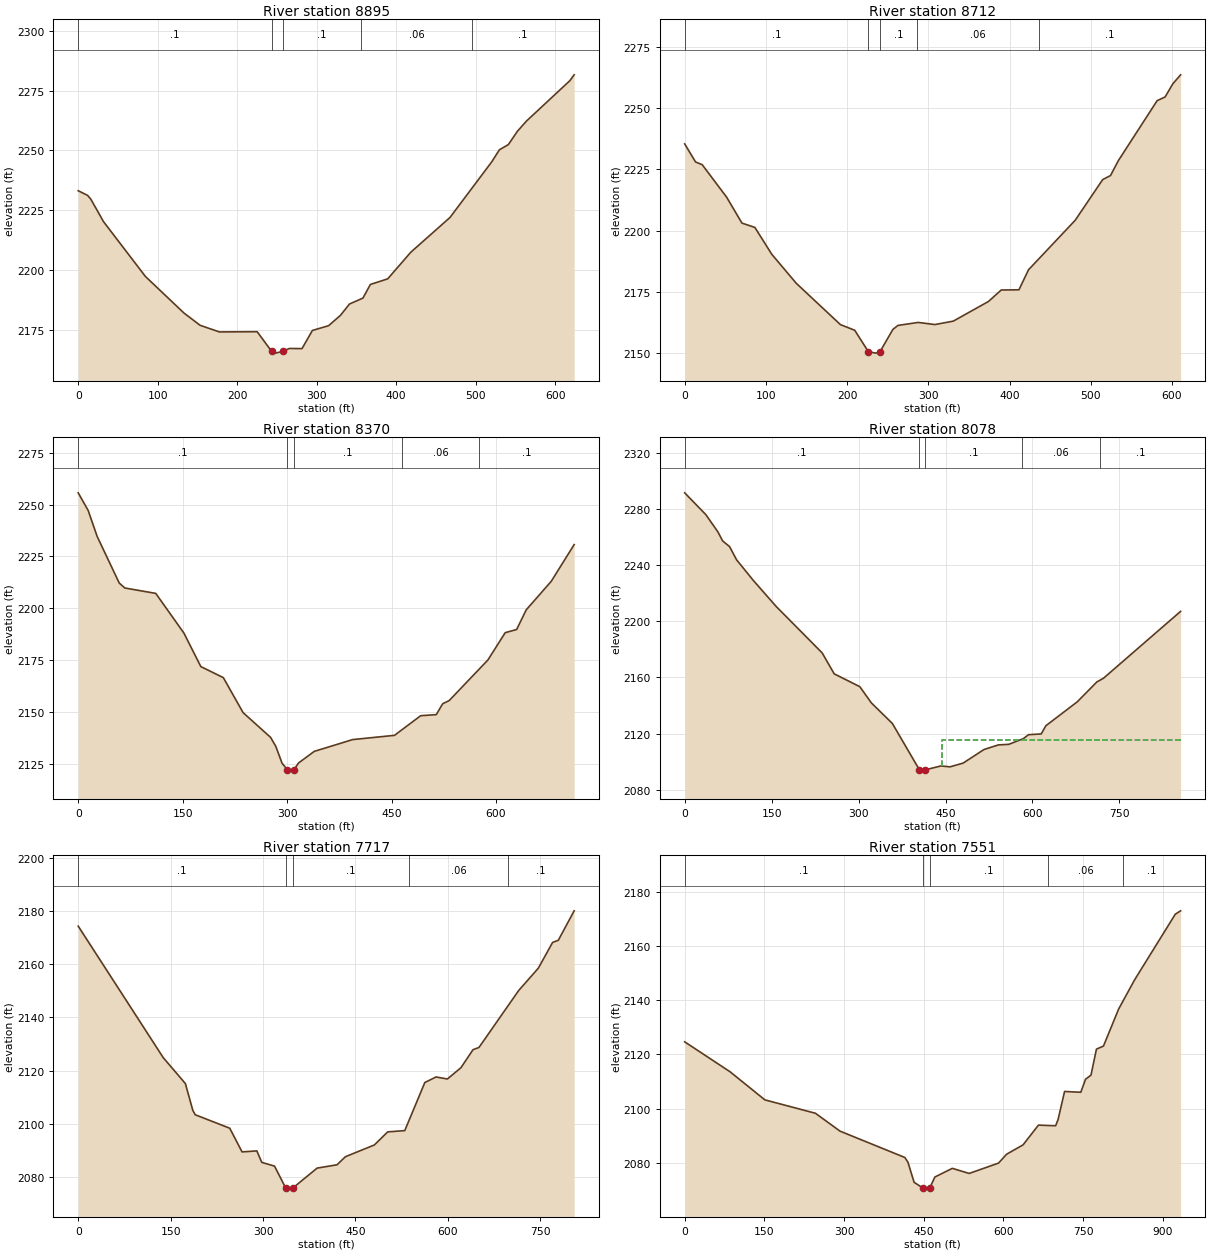
Type RM Length L Ch R = 1 ,8895    ,181,182.7,183
XS GIS Cut Line= 4
2237561.43326734684925.6269973582237591.81897173685124.954153697
2237644.23127569685214.4101198382237869.38343174685439.661646184
#Sta/Elev= 30
       0 2233.16    11.7 2231.24    15.7 2229.72    31.9  2220.2    84.5 2197.33
   133.1    2182   153.3  2176.9   177.6 2174.12   225.1 2174.22  243.262166.013
   248.3 2165.26  257.112166.012   265.6 2167.21   281.5 2167.15   294.6 2174.75
   314.9 2176.72   329.9 2181.07   341.2 2185.79   358.1 2188.26   367.5 2193.97
   389.3 2196.32   418.4 2207.47   467.6 2221.97   520.2 2245.27   529.8 2250.28
   541.1 2252.46   552.4 2258.01   563.7 2262.25   618.4 2279.17   623.8 2281.62
#Mann= 5 ,-1,0
       0      .1       0  243.26    .045       0  257.11      .1       0
  355.31     .06       0  495.31      .1       0
Bank Sta=243.26,257.11
XS Rating Curve= 0 ,0
Exp/Cntr=0.3,0.1

Type RM Length L Ch R = 1 ,8712    ,342.4,342.5,341
XS GIS Cut Line= 4
2237395.52239837684976.0431672452237435.96309421685177.637830605
2237457.35746246685234.1926852492237648.37324802685521.078158697
#Sta/Elev= 30
       0 2235.35    13.4 2227.97    21.6 2226.86    51.7 2213.59    70.5 2203.03
    86.5 2201.24   107.2 2190.33   137.4 2178.46   191.8 2161.59   209.4 2159.29
  226.14 2150.59   235.1 2149.96   240.6 2150.57   256.4 2159.65   262.7 2161.27
   287.6 2162.49   308.1 2161.62   330.8 2163.02   374.1 2171.04   389.8 2175.72
   411.6  2175.8   423.4 2183.97   480.9 2204.18   514.7 2220.76   524.4 2222.44
     534 2228.49   581.8 2252.99   591.6  2254.5   601.2 2259.91   610.7 2263.53
#Mann= 5 ,-1,0
       0      .1       0  226.14    .045       0   240.6      .1       0
  286.08     .06       0  436.08      .1       0
Bank Sta=226.14,240.6
XS Rating Curve= 0 ,0
Exp/Cntr=0.3,0.1

Type RM Length L Ch R = 1 ,8370    ,290.2,291.7,290.8
XS GIS Cut Line= 3
2237083.21526953685015.0664286272237122.72802721685277.387236564
2237345.53607747685664.831777158
#Sta/Elev= 30
       0 2255.65    14.3 2247.16    27.3 2234.58    58.9 2212.23    66.9 2209.83
   111.4 2207.22   151.8  2188.1   176.1 2171.98   208.4 2166.66   236.8  2149.8
   276.2 2137.92   283.8 2133.55   292.7 2125.48   300.3 2122.31   306.6 2121.64
  309.93 2122.31   316.3 2125.53   338.9 2131.14   394.2 2136.83   454.2 2138.87
   491.8 2148.33   514.2 2148.84   523.4 2154.08   532.7  2155.6   588.4 2175.19
   613.2 2188.31   629.6 2189.84   643.4 2199.31   679.3 2213.03   712.2 2230.72
#Mann= 5 ,-1,0
       0      .1       0   300.3    .045       0  309.93      .1       0
  465.28     .06       0  575.28      .1       0
Bank Sta=300.3,309.93
XS Rating Curve= 0 ,0
Exp/Cntr(USF)=0,0
Exp/Cntr=0.3,0.1

Type RM Length L Ch R = 1 ,8078    ,360.5,361.1,360.3
XS GIS Cut Line= 4
2236857.92228138684992.0126267552236889.27498328685383.366353754
2236983.70861699685564.0270698122237166.85658779685747.344930315
#Sta/Elev= 30
       0 2291.34    36.6 2275.78    57.3 2263.55    65.4 2257.16    77.4 2253.09
    89.5  2243.7   118.3 2229.05   157.7 2210.53   237.2  2177.4     258 2162.49
   302.1 2153.39   322.2 2141.77   358.3 2127.19  405.042094.148   408.2 2093.26
  414.862094.148     442 2096.94   457.8 2096.31   480.4 2098.97   516.5 2108.67
   541.3 2111.92   559.1 2112.33   584.2 2116.35   593.2 2119.18   615.1 2119.74
   623.1 2125.56   677.2 2142.55   711.2 2156.77   722.5 2159.36   855.6 2206.98
#Mann= 5 ,-1,0
       0      .1       0  405.04    .045       0  414.86      .1       0
  582.61     .06       0  716.46      .1       0
#XS Ineff= 2 , 0
                          444.06         2115.67
Permanent Ineff=
       F       F
Bank Sta=405.04,414.86
XS Rating Curve= 0 ,0
Exp/Cntr=0.3,0.1

Type RM Length L Ch R = 1 ,7717    ,165.5,166.2,166.2
XS GIS Cut Line= 4
2236606.19518291685251.175462956 2236600.7072999685565.082371199
2236691.80615788685724.2309785252236958.51727223685877.891702839
#Sta/Elev= 30
       0 2174.29     138 2124.86     174 2115.09     186 2105.06     190 2103.37
     246 2098.31     266 2089.41     290 2089.78     298 2085.47   318.7 2084.07
  336.872075.815   341.7 2075.41  348.332075.815   387.8 2083.31   420.1 2084.56
   433.8  2087.6   480.7 2092.01   502.4 2096.93   530.1 2097.41   562.7 2115.49
   580.9 2117.58   599.3 2116.82   621.3 2121.05   640.9 2127.83   650.6 2128.68
     715 2150.07     747  2158.5   770.1 2168.17   779.4 2168.98   805.1 2180.05
#Mann= 5 ,-1,0
       0      .1       0  336.87    .045       0  348.33      .1       0
  537.33     .06       0  697.33      .1       0
Bank Sta=336.87,348.33
XS Rating Curve= 0 ,0
Exp/Cntr(USF)=0,0
Exp/Cntr=0.3,0.1

Type RM Length L Ch R = 1 ,7551    ,351.2,344.9,337.2
XS GIS Cut Line= 4
     2236235.102      685309.5552236468.43150928  685643.1572005
2236512.59370984685729.652026333     2236848.016      685997.456
#Sta/Elev= 30
       0  2124.6    85.6 2113.54   150.9 2103.21   246.1 2098.27   292.4 2091.68
   414.4 2081.97   420.3 2080.17   431.8 2072.82  448.482070.725   454.3 2070.31
  461.222070.725   470.9 2074.77   503.7 2077.97   535.5 2076.09   590.7  2079.9
     606 2083.19   636.8 2086.61   665.8  2093.9   698.2 2093.67   702.8 2095.99
     715  2106.3   745.5 2106.01   754.5 2110.82   764.7 2112.32     775 2121.91
   788.2 2123.04   816.7 2136.66   846.6 2147.38   923.4 2171.64   933.4 2172.88
#Mann= 5 ,-1,0
       0      .1       0  448.48    .045       0  461.22      .1       0
  684.22     .06       0  824.22      .1       0
Bank Sta=448.48,461.22
XS Rating Curve= 0 ,0
Exp/Cntr=0.3,0.1

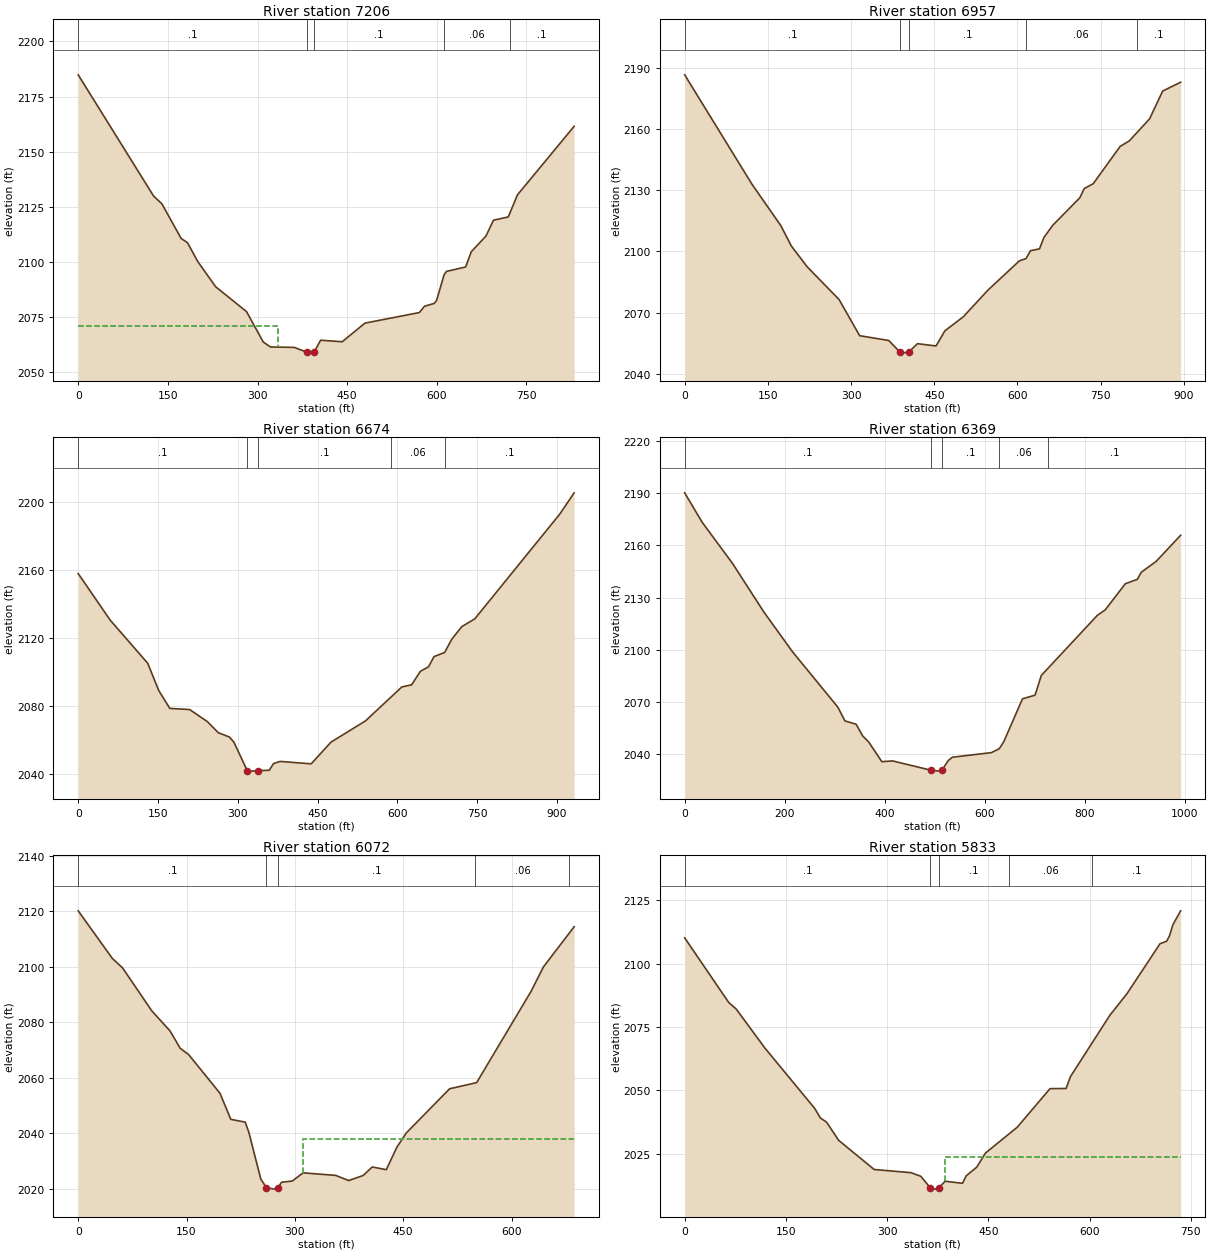
Type RM Length L Ch R = 1 ,7206    ,244.4,248.7,252.4
XS GIS Cut Line= 4
2235977.68064128685852.7545188732236239.61476931685954.535661122
2236371.03248047685950.6822786372236774.79296051686055.980237397
#Sta/Elev= 30
       0 2184.86   125.9 2130.03     140 2126.42   172.2 2110.74   182.9 2108.79
     200 2100.26   230.1 2088.81   281.6  2077.6   309.6 2063.81   321.6 2061.56
   361.6 2061.36  382.572059.203   385.6 2058.77  394.612059.201   405.6 2064.62
   441.7 2063.93   479.8 2072.36   570.8 2077.16   579.4 2080.02   595.6 2081.29
   599.7 2082.68   612.1 2094.21   616.2  2095.8   648.3 2097.81   657.6 2104.68
   682.4 2111.88   694.8 2118.99   719.6 2120.47   734.9 2130.46   829.8 2161.55
#Mann= 5 ,-1,0
       0      .1       0  382.57    .045       0  394.61      .1       0
  612.49     .06       0  722.49      .1       0
#XS Ineff= 2 , 0
          334.19 2070.84
Permanent Ineff=
       F       F
Bank Sta=382.57,394.61
XS Rating Curve= 0 ,0
Exp/Cntr=0.3,0.1

Type RM Length L Ch R = 1 ,6957    ,286,283.5,279.6
XS GIS Cut Line= 3
2235934.09611226685967.4962287982236343.05315426686228.280429492
2236748.05892049 686285.57392813
#Sta/Elev= 30
       0 2186.44   121.5  2132.8   173.3 2112.62   192.2 2102.67   220.7 2092.49
   278.4  2076.4   315.5  2058.7   367.8 2056.37  387.892050.756   391.5 2050.17
  404.252050.757   419.7  2054.8   453.2 2053.67   469.1 2061.09   502.3 2067.96
     547  2081.1   603.3 2095.32   615.4 2096.47   623.5 2100.32   639.7 2101.24
   647.8 2106.88   663.9 2112.85   712.4 2126.25   720.5 2130.79   736.6 2133.14
   785.1 2151.41   801.3 2154.02   838.2  2164.9   861.7 2178.48   894.1 2182.81
#Mann= 5 ,-1,0
       0      .1       0  387.89    .045       0  404.25      .1       0
  615.03     .06       0  815.03      .1       0
Bank Sta=387.89,404.25
XS Rating Curve= 0 ,0
Exp/Cntr(USF)=0,0
Exp/Cntr=0.3,0.1

Type RM Length L Ch R = 1 ,6674    ,301.3,305.1,303.3
XS GIS Cut Line= 3
2235802.23019227686326.8936657172236263.48619227686455.229665717
2236706.57319227686553.031665717
#Sta/Elev= 30
       0 2158.01    60.1 2130.67   130.7 2105.29   151.5 2089.22   172.2 2078.75
   209.6 2078.07   242.8    2071   263.3 2064.49   284.4  2061.9   292.7 2058.94
  317.822042.178   325.9 2041.87  338.842042.178   359.1 2042.38   367.4 2046.32
   379.8 2047.58     438 2046.15   475.3 2058.91   540.2 2071.42   608.5 2091.36
   626.9 2092.61   643.3 2100.53   658.8 2103.25   668.9 2109.18     689 2111.65
   702.5 2119.46   721.2 2126.81   745.7 2131.42   905.5    2193   932.5 2205.49
#Mann= 5 ,-1,0
       0      .1       0  317.82    .045       0  338.84      .1       0
  588.78     .06       0  688.78      .1       0
Bank Sta=317.82,338.84
XS Rating Curve= 0 ,0
Exp/Cntr=0.3,0.1

Type RM Length L Ch R = 1 ,6369    ,290,296.7,299
XS GIS Cut Line= 4
2235641.13497498686425.3975654122235904.15254038 686638.73700283
2236229.46246816686761.878754832 2236534.7643762686758.241854931
#Sta/Elev= 30
       0 2190.17    34.8 2173.34    95.9 2149.53   158.4 2121.68   215.5  2098.9
   306.3 2067.03   320.5 2059.13     343 2057.19   355.8 2050.58   368.2 2046.95
   394.3  2035.7   415.7 2036.14  493.312030.746   509.8 2030.27  514.492030.747
   526.9 2036.29   535.4 2038.26   613.6 2040.91   629.1 2043.13   638.1 2047.13
   675.6 2071.83   700.7 2073.92   713.2 2085.25   825.2 2119.74   841.2 2122.98
   881.2 2137.94   905.2 2140.47   913.2 2144.56   942.9 2150.78   991.8 2165.77
#Mann= 5 ,-1,0
       0      .1       0  493.31    .045       0  514.49      .1       0
  628.66     .06       0   726.5      .1       0
Bank Sta=493.31,514.49
XS Rating Curve= 0 ,0
Exp/Cntr=0.3,0.1

Type RM Length L Ch R = 1 ,6072    ,240.1,239.2,239.3
XS GIS Cut Line= 2
2235631.36887286686691.8884304492236179.99798879687104.832618643
#Sta/Elev= 30
       0 2120.17    47.2 2103.04    61.5 2099.58   101.9 2084.12   127.2 2076.88
   141.2 2070.64   152.9 2068.37   196.3 2054.43   211.3 2045.03   231.3 2044.02
   236.3 2040.33   252.9 2023.45  260.532020.438   271.4 2019.88  276.672020.438
   281.5 2022.36   296.4  2022.8   311.4 2025.75   356.5 2024.83   374.6 2022.97
   394.6  2024.8   407.1 2027.86   426.6 2026.89   441.1 2034.93   454.4 2040.16
   514.3 2056.05   551.7 2058.26   627.1 2091.18   644.2 2099.96   686.7 2114.45
#Mann= 5 ,-1,0
       0      .1       0  260.53    .045       0  276.67      .1       0
     550     .06       0     680      .1       0
#XS Ineff= 2 , 0
                          310.83         2037.88
Permanent Ineff=
       F       F
Bank Sta=260.53,276.67
XS Rating Curve= 0 ,0
Exp/Cntr(USF)=0,0
Exp/Cntr=0.3,0.1

Type RM Length L Ch R = 1 ,5833    ,311.4,308.7,305.6
XS GIS Cut Line= 3
2235505.73223376686848.3741338592235941.47014485687206.184106191
2236103.91148199687259.965359701
#Sta/Elev= 30
       0 2110.13    65.3 2084.62    76.2 2082.11   118.8  2066.7   192.7 2042.87
   201.2 2039.07   210.2 2037.49   228.2 2030.29   280.8  2018.8   335.3 2017.55
   349.9 2016.12  363.65 2011.67   370.6 2011.06   376.82011.671     386 2014.18
   411.6 2013.35   417.2 2016.31   432.8 2019.72   445.7 2025.27   492.9 2035.49
   541.4 2050.68   565.2 2050.73   571.5 2055.34   629.9 2079.54   655.2 2088.03
   704.4  2107.8   714.1 2108.77   718.4 2110.88   723.4 2115.24   734.9 2120.77
#Mann= 5 ,-1,0
       0      .1       0  363.65    .045       0   376.8      .1       0
     480     .06       0  603.82      .1       0
#XS Ineff= 2 , 0
                           386.2         2023.85
Permanent Ineff=
       F       F
Bank Sta=363.65,376.8
XS Rating Curve= 0 ,0
Exp/Cntr(USF)=0,0
Exp/Cntr=0.3,0.1

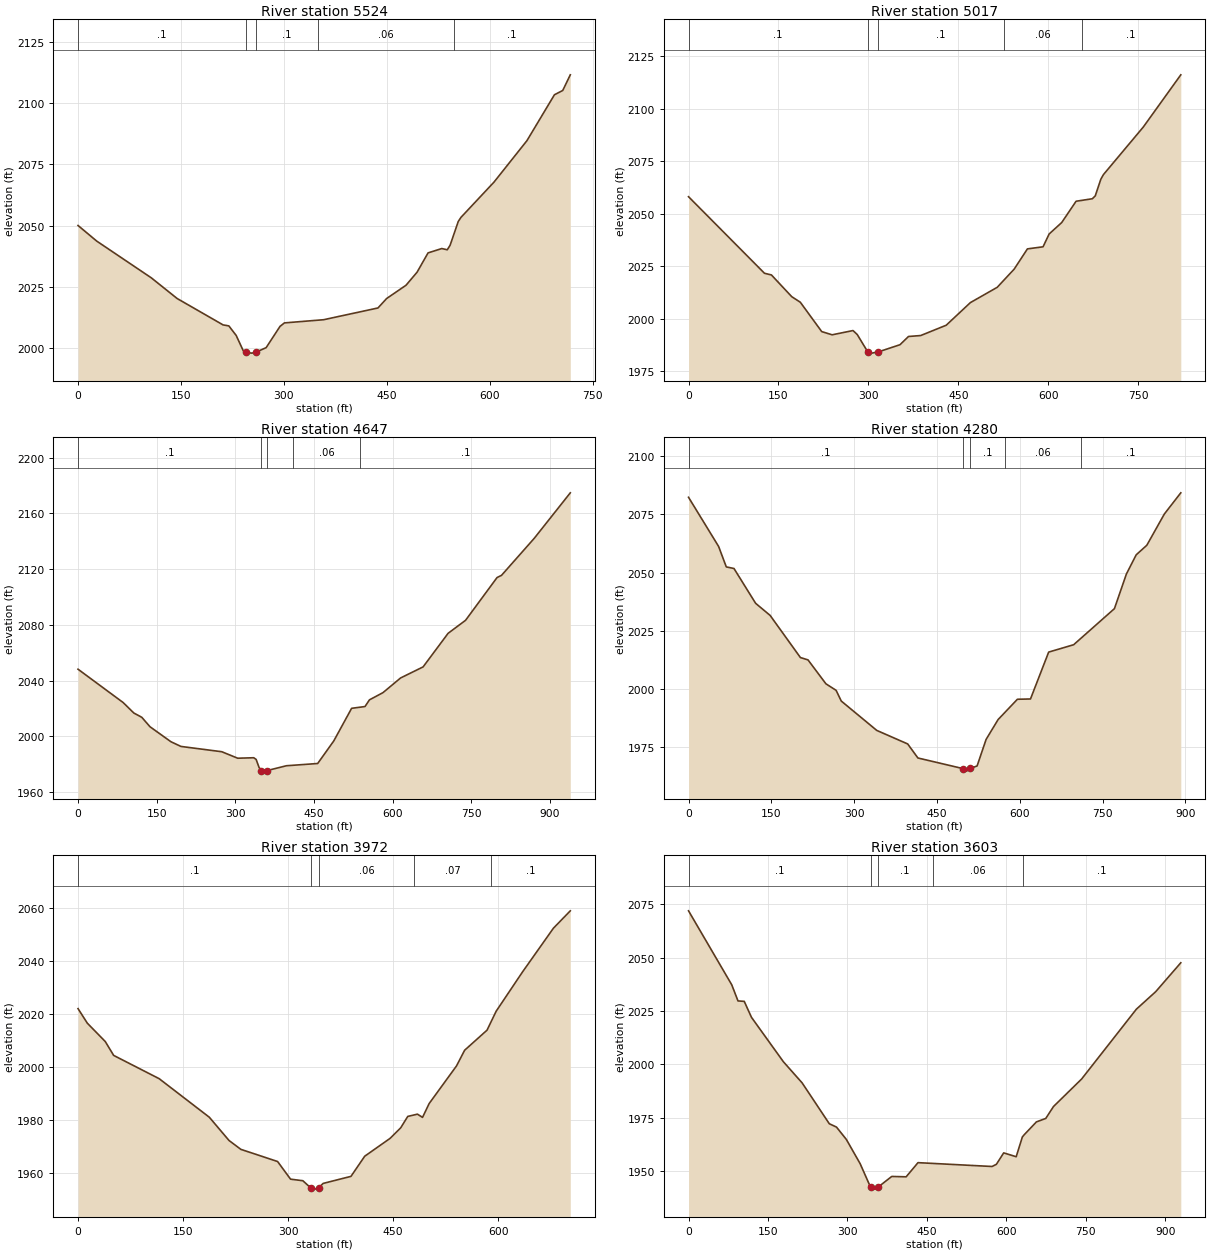
Type RM Length L Ch R = 1 ,5524    ,501.2,506.9,511.8
XS GIS Cut Line= 3
2235346.19583845687230.9647912532235688.20047915687336.545398373
2236047.23875768687353.551203254
#Sta/Elev= 30
       0 2050.01    27.2 2043.63   106.7  2028.6   144.4 2020.13   211.4 2009.32
   219.8 2008.91   230.5    2005   240.7 1998.81  244.43 1998.11   253.2 1997.77
  259.08 1998.11   274.2 2000.03   294.4 2008.73   300.8 2010.14   357.9 2011.44
   437.1 2016.25   449.7 2020.11     478 2025.55   494.1 2030.89   510.1 2038.79
   530.1 2040.57   538.1 2040.07   542.2  2041.9   554.1 2051.63   558.1 2053.34
   606.2 2067.76   654.2 2084.72   694.3 2103.51   706.4 2105.27   717.4 2111.67
#Mann= 5 ,-1,0
       0      .1       0  244.43    .045       0  259.08      .1       0
     350     .06       0  547.93      .1       0
Bank Sta=244.43,259.08
XS Rating Curve= 0 ,0
Exp/Cntr=0.3,0.1

Type RM Length L Ch R = 1 ,5017    ,369.3,369.7,365
XS GIS Cut Line= 3
2235158.05371312687384.2282284852235371.69792757687717.213902544
2235653.69072981688036.055576602
#Sta/Elev= 30
       0 2058.06   126.7 2021.66   138.3 2020.86   172.2 2010.53   186.5 2007.89
   222.2 1993.93   239.6  1992.4   274.4 1994.42   281.5 1992.53  299.111984.237
   305.3 1983.69  316.321984.237   352.8 1987.69     367  1991.6   387.3 1992.05
   429.9 1996.95   470.3 2007.72     515 2014.98   543.3 2023.62   565.4 2033.25
   591.5 2034.24   601.6 2040.32   622.6 2045.77   646.6  2055.9   673.7 2057.09
   678.6 2058.47   687.8 2066.32   692.2 2068.56   758.7 2091.18   821.3 2116.01
#Mann= 5 ,-1,0
       0      .1       0  299.11    .045       0  316.32      .1       0
  525.63     .06       0  655.63      .1       0
Bank Sta=299.11,316.32
XS Rating Curve= 0 ,0
Exp/Cntr=0.3,0.1

Type RM Length L Ch R = 1 ,4647    ,368.6,367.9,367.4
XS GIS Cut Line= 3
2234899.13204741 687589.413064092235194.07004741 687966.04006409
2235507.01104741 688303.65606409
#Sta/Elev= 30
       0 2048.19      86 2024.29   106.4 2016.77   121.6 2013.68   137.3  2006.9
   177.2 1996.16   196.3 1992.79   274.1    1989   304.5 1984.34     335 1984.68
   339.6  1983.5   345.3 1977.63  349.831975.505   355.3 1975.08  360.811975.506
   397.4 1978.94     457 1980.55   487.7 1996.74   521.7 2020.14   547.2 2021.41
   555.7 2026.21   581.5 2031.38   615.1 2041.91     658 2049.85   705.7 2073.94
     739 2083.28     799 2113.93   807.6 2115.55   869.9 2142.06   938.7 2174.72
#Mann= 5 ,-1,0
       0      .1       0  349.83    .045       0  360.81      .1       0
     410     .06       0  538.37      .1       0
Bank Sta=349.83,360.81
XS Rating Curve= 0 ,0
Exp/Cntr=0.3,0.1

Type RM Length L Ch R = 1 ,4280    ,302.6,307.1,305.3
XS GIS Cut Line= 4
2234573.24106409687634.0442144452234785.81201119687999.858194913
 2234899.5809157688123.8719243722235120.76533998 688326.76573245
#Sta/Elev= 30
       0 2082.39    54.5 2061.22    68.4 2052.41    82.3 2051.74   121.5 2036.75
   147.8 2031.53   202.6  2013.4   216.4 2012.38   248.8  2002.1   267.3 1999.27
   276.6 1994.67   340.9 1982.03   396.9  1976.2   415.4 1970.16   496.5 1965.62
   503.5  1964.5   510.6 1965.65   522.6 1966.73   538.9 1978.15   560.6 1986.69
   595.6 1995.44   619.3 1995.56   652.2 2015.74   697.5 2018.92   771.3 2034.45
     793 2049.37   810.7 2057.61     830 2061.75   861.7 2075.19   891.5 2084.31
#Mann= 5 ,-1,0
       0      .1       0   496.5    .045       0   510.6      .1       0
  573.09     .06       0  711.39      .1       0
Bank Sta=496.5,510.6
XS Rating Curve= 0 ,0
Exp/Cntr=0.3,0.1

Type RM Length L Ch R = 1 ,3972    ,368.8,369.1,370
XS GIS Cut Line= 2
2234404.86290171687933.877393479  2234837.308083688488.153577612
#Sta/Elev= 30
       0 2021.87    13.3 2016.37    38.9 2009.45    50.9 2004.21   115.9 1995.42
   187.5 1980.87   215.6  1972.1   232.5 1968.75     285 1964.15   303.5 1957.49
   321.1  1956.9  332.221954.212   338.2 1953.73  343.521954.212     350 1955.88
   389.8 1958.55   409.4 1966.15   445.6 1972.88   460.8 1976.87   470.9 1981.18
   484.7 1982.03     492 1980.82   501.4 1986.02   540.5 2000.24   552.1 2006.16
   584.1 2013.74   597.1 2020.88   634.5 2035.62   678.9 2052.23     703 2058.79
#Mann= 5 ,-1,0
       0      .1       0  332.22    .045       0  343.52     .06       0
     480     .07       0     590      .1       0
Bank Sta=332.22,343.52
XS Rating Curve= 0 ,0
Exp/Cntr(USF)=0,0
Exp/Cntr=0.3,0.1

Type RM Length L Ch R = 1 ,3603    ,436.5,435.3,436.6
XS GIS Cut Line= 3
2234100.11986633687994.8006685662234312.62786633688392.374668566
2234545.72686633688810.467668566
#Sta/Elev= 30
       0 2071.93    81.6 2037.26    93.4 2029.69   105.2 2029.49   118.9 2021.99
   179.1 2001.19   214.6 1991.24   265.8 1972.12   279.4 1970.55     298 1964.76
     324 1953.42  343.751942.343   347.6 1941.47  357.561942.346   383.7 1947.41
   410.9 1947.24   433.3 1953.88   573.1 1952.08   581.3 1953.11   595.1 1958.46
   618.7 1956.66   630.3  1965.9   633.4 1966.85   656.9 1972.99   674.5  1974.6
   689.2 1980.21   742.2 1993.08   845.6 2025.82   882.2 2034.05   929.5 2047.58
#Mann= 5 ,-1,0
       0      .1       0  343.75    .045       0  357.56      .1       0
   460.8     .06       0   630.8      .1       0
Bank Sta=343.75,357.56
XS Rating Curve= 0 ,0
Exp/Cntr=0.3,0.1

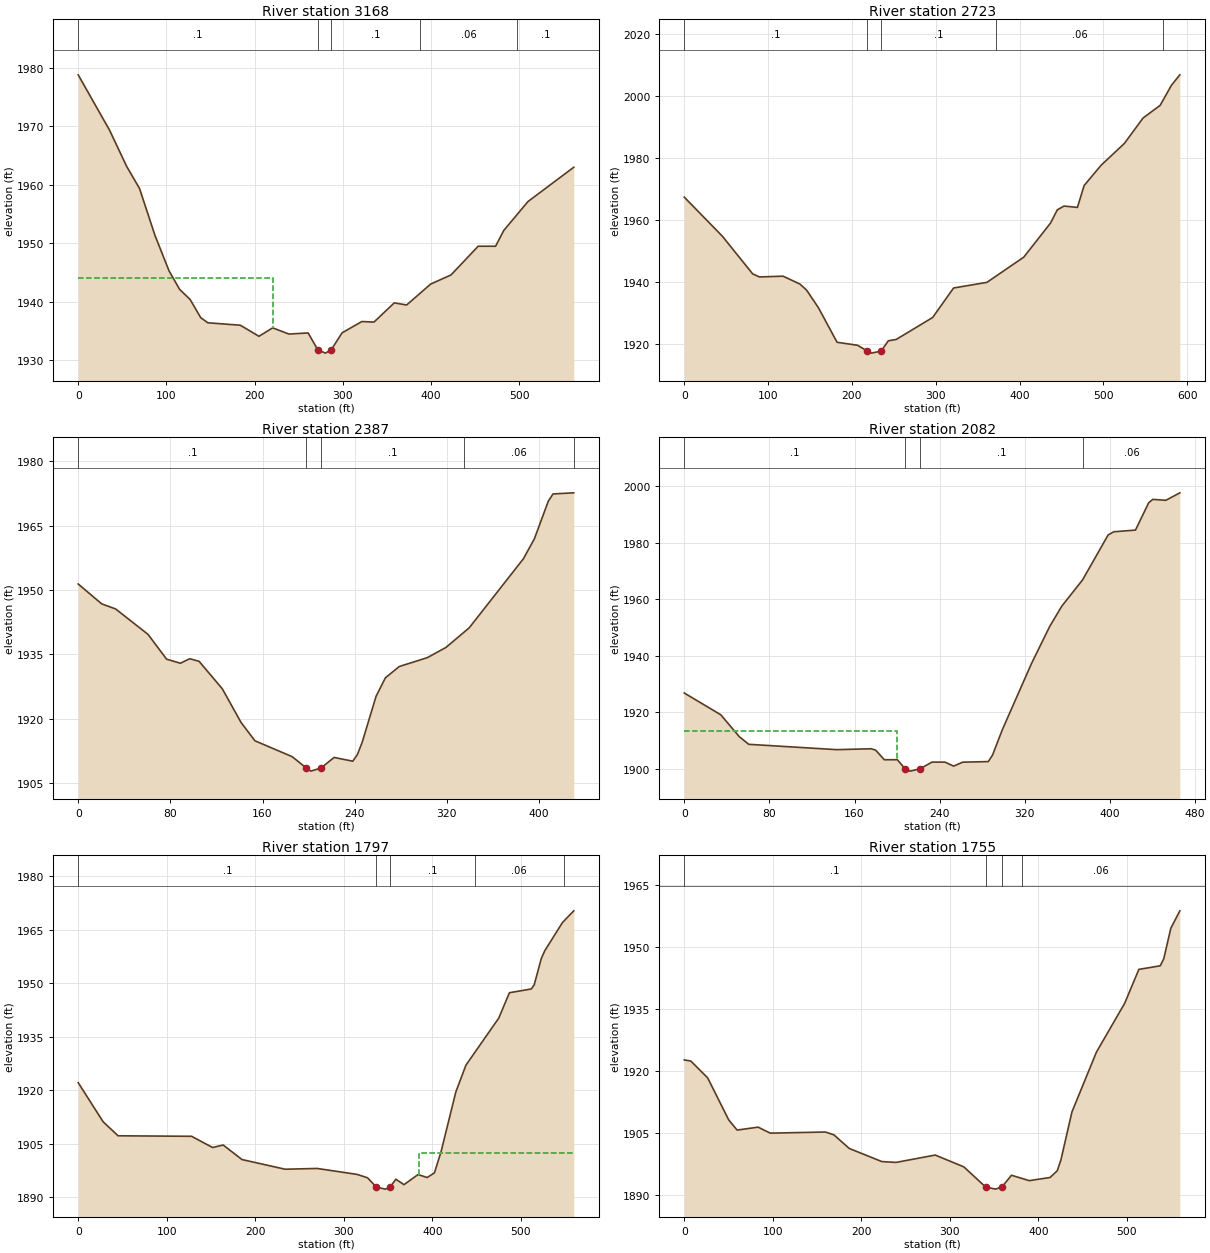
Type RM Length L Ch R = 1 ,3168    ,439.9,444.9,450.6
XS GIS Cut Line= 3
2233907.92171042688338.1764791872233912.26176484688515.701289837
2234101.49311143688850.382573712
#Sta/Elev= 30
       0 1978.77    35.6  1969.3      55 1963.11    69.6 1959.33      87 1951.35
     103 1945.27     115  1942.1     127 1940.35     139 1937.25     147 1936.38
   183.9 1935.96     205 1934.07   220.6 1935.51     239 1934.45   260.8 1934.64
  271.681931.777   280.4 1931.19  287.141931.777   299.3 1934.66   321.7 1936.59
   335.5  1936.5   358.5 1939.78   372.5 1939.42   399.8    1943   422.8 1944.55
   453.7 1949.47   473.4 1949.46   482.6 1952.14   510.1  1957.1   562.1 1962.97
#Mann= 5 ,-1,0
       0      .1       0  271.68    .045       0  287.14      .1       0
  387.58     .06       0  497.58      .1       0
#XS Ineff= 2 , 0
          221.14 1944.01
Permanent Ineff=
       F       F
Bank Sta=271.68,287.14
XS Rating Curve= 0 ,0
Exp/Cntr=0.3,0.1

Type RM Length L Ch R = 1 ,2723    ,339,336,333.8
XS GIS Cut Line= 4
2233544.17702061688427.8699088592233558.61243819688587.194034499
2233526.79891538688755.7458087192233516.70155016689015.206750275
#Sta/Elev= 30
       0 1967.38    45.5 1954.75    81.6 1942.61    89.7 1941.62   117.8 1941.87
   137.9 1939.34   145.9 1937.38     160  1931.7   182.3 1920.53   206.8 1919.56
  218.471917.688   223.1 1917.03  234.881917.688   243.4 1921.01   252.8 1921.44
   296.3 1928.53   321.3 1938.06     361 1939.87     405 1948.01     437 1959.04
     445 1963.28     453  1964.5     469 1964.06     477 1971.13   497.2 1977.66
   525.1 1984.74   547.3 1992.92   567.7 1997.01   581.1 2003.48   591.2 2006.86
#Mann= 5 ,-1,0
       0      .1       0  218.47    .045       0  234.88      .1       0
   371.5     .06       0   571.5      .1       0
Bank Sta=218.47,234.88
XS Rating Curve= 0 ,0
Exp/Cntr(USF)=0,0
Exp/Cntr=0.3,0.1

Type RM Length L Ch R = 1 ,2387    ,304.9,304.8,304.7
XS GIS Cut Line= 3
2233188.87335648688468.8682870412233197.11928958688553.506192146
2233246.42222832688895.003100162
#Sta/Elev= 30
       0 1951.38    20.4 1946.75    32.5 1945.56    60.6 1939.64    76.7 1933.86
    88.7 1932.91    96.8 1933.96   104.9 1933.36   125.1 1926.94   141.3 1919.12
   153.4 1914.83   185.7 1911.13  198.111908.461   201.9 1907.76  210.611908.463
   222.1 1910.95   238.3 1910.07   242.3 1911.63   246.4 1914.44   258.5 1925.19
   266.6 1929.51   278.7 1932.15     303 1934.21   319.1 1936.58   339.3 1941.15
   386.4 1957.27   395.9 1961.91     408 1970.69   412.1 1972.37   430.1 1972.63
#Mann= 5 ,-1,0
       0      .1       0  198.11    .045       0  210.61      .1       0
  335.04     .06       0  430.08      .1       0
Bank Sta=198.11,210.61
XS Rating Curve= 0 ,0
Exp/Cntr=0.3,0.1

Type RM Length L Ch R = 1 ,2082    ,275,284.9,293.4
XS GIS Cut Line= 3
2232964.63177441688537.9471143452232909.31625904688660.655484638
2232969.72342338688986.223116886
#Sta/Elev= 30
       0 1926.82    34.3 1919.12    51.8 1911.35    60.6 1908.68   143.3 1906.79
   175.8  1907.1   179.9  1906.6     188 1903.22   200.2 1903.24  207.521900.016
   212.4  1899.2  221.541900.019   232.8 1902.39     245 1902.38   253.1 1900.97
   261.6 1902.37   285.7 1902.57   289.7  1904.9   298.8 1913.78   326.3 1937.26
   343.4 1950.36   354.8 1957.55   374.3 1966.82   398.3  1982.7   403.6 1983.82
     424 1984.42   436.4 1994.08   440.3 1995.28   452.5 1994.94   465.7 1997.59
#Mann= 4 ,-1,0
       0      .1       0  207.52    .045       0  221.54      .1       0
   374.6     .06       0
#XS Ineff= 2 , 0
          200.18 1913.24
Permanent Ineff=
       F       F
Bank Sta=207.52,221.54
XS Rating Curve= 0 ,0
Exp/Cntr=0.3,0.1

Type RM Length L Ch R = 1 ,1797    ,41.3,42,42.3
XS GIS Cut Line= 6
2232930.77306294688549.4360969632232839.44829631688691.624960943
2232687.08445199688697.8528307632232644.95743148688721.184719046
2232627.45851527 688774.329575692232623.56986722688905.895501285
#Sta/Elev= 30
       0 1922.14    28.2 1911.17    45.1 1907.26   128.1 1907.12   151.8 1903.98
   163.8 1904.68     185 1900.61   233.8  1897.9   269.8 1898.12   314.9 1896.46
   326.8 1895.51  336.851892.889   346.9 1892.33  352.321892.888   358.8  1895.1
     368 1893.58   383.9 1896.41   394.2 1895.58   402.4 1896.89   409.9 1902.82
   426.6 1919.56     438 1927.04   475.1 1940.23   487.1 1947.31   511.9 1948.37
   515.1 1949.54   523.1 1956.89   527.1  1959.1   547.1 1966.99   559.8 1970.24
#Mann= 5 ,-1,0
       0      .1       0  336.85    .045       0  352.32      .1       0
   448.2     .06       0   548.2      .1       0
#XS Ineff= 2 , 0
                          385.17         1902.45
Permanent Ineff=
       F       F
Bank Sta=336.85,352.32
XS Rating Curve= 0 ,0
Exp/Cntr=0.3,0.1

Type RM Length L Ch R = 1 ,1755    ,170.2,160.5,152.8
XS GIS Cut Line= 6
2232904.20063462688518.9750205932232812.87586799688661.163884574
2232660.51202367688667.3917543932232618.38500316688690.723642676
2232600.88608694 688743.86849932 2232596.9974389688875.434424916
#Sta/Elev= 30
       0 1922.74     7.4 1922.46    26.4  1918.4    50.2 1908.23    59.7 1905.77
    83.4 1906.48    97.1 1905.03   159.5  1905.3     169 1904.62   186.4 1901.32
   223.2 1898.15   239.2 1897.95   283.5 1899.73   315.8 1896.87  340.281892.022
   351.6 1891.49  358.851892.022   369.6 1894.85   389.7 1893.54   413.2 1894.31
   421.3 1895.93   425.4 1898.53   437.9 1910.16   465.5 1924.59   497.5 1936.45
   513.5 1944.63   537.6 1945.49   541.6 1947.19   549.6 1954.58   559.8 1958.79
#Mann= 4 ,-1,0
       0      .1       0  340.28    .045       0  358.85      .1       0
  381.67     .06       0
Bank Sta=340.28,358.85
XS Rating Curve= 0 ,0
Exp/Cntr=0.3,0.1