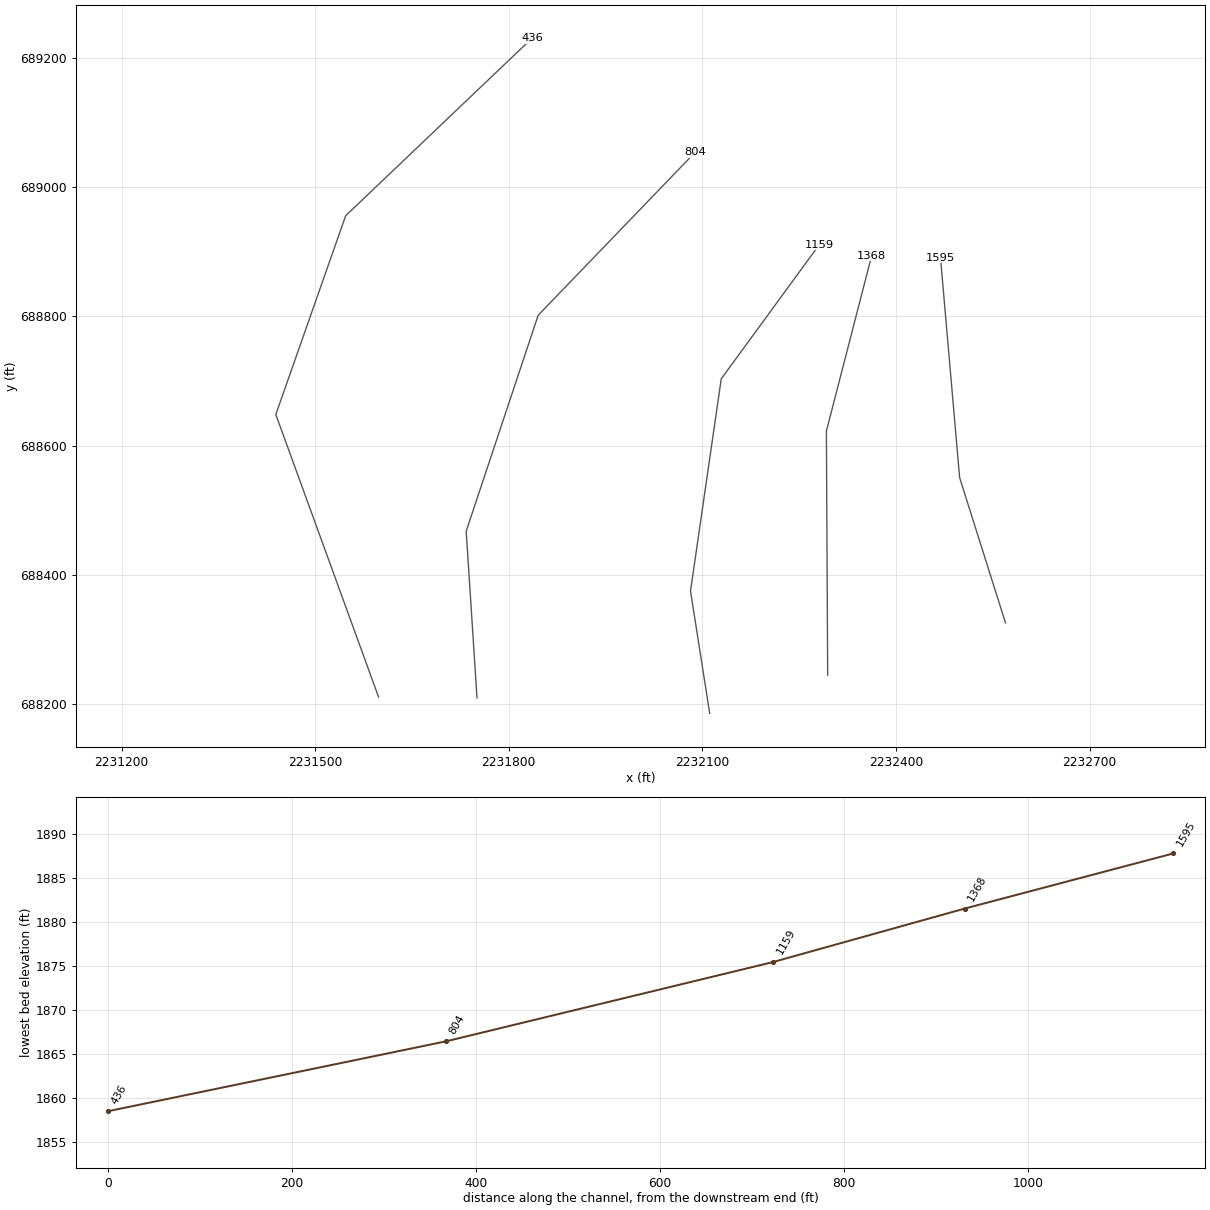
HEC-RAS study KETTLERN.prj: KETTLERN

--- KETTLERN.g01 (geometry) --- (continued)

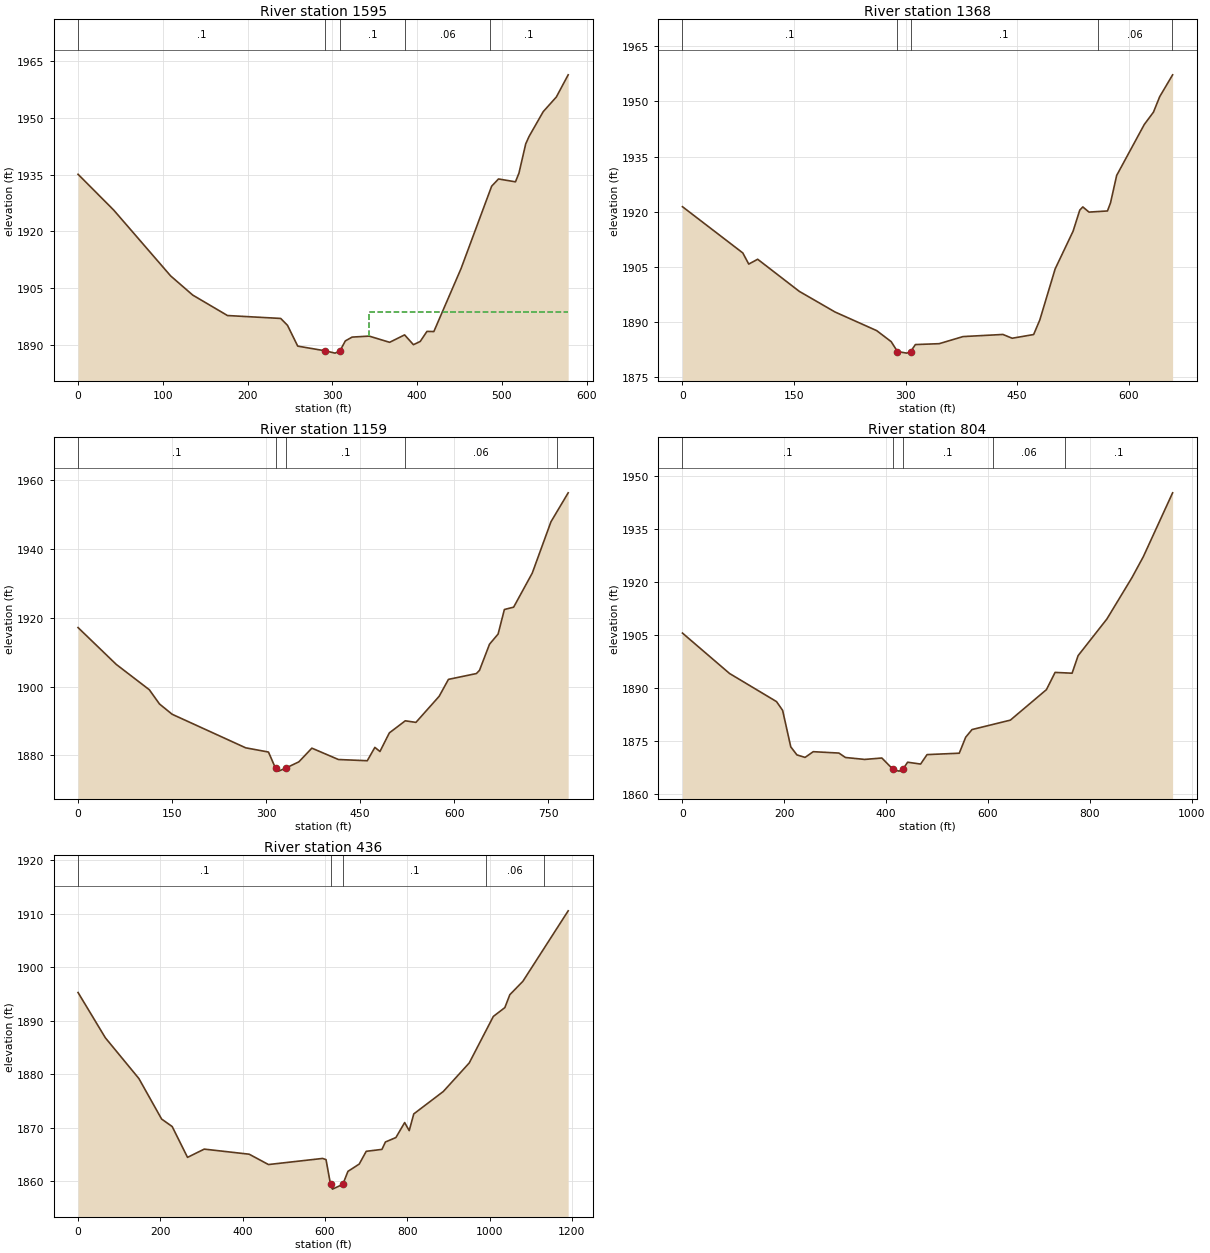
Type RM Length L Ch R = 1 ,1595    ,225.8,227,224.3
XS GIS Cut Line= 3
2232569.81582263688325.0522340282232498.69285881688550.274952808
2232469.05829055688891.072487805
#Sta/Elev= 30
       0 1935.08    42.1 1925.61   109.2 1908.22   135.3 1903.14   176.3 1897.73
   239.1 1896.96   247.1 1895.15   259.2 1889.64   291.3 1888.41   303.3 1887.79
  309.07 1888.41   315.4 1891.03   323.4 1892.03   343.5 1892.29   367.6 1890.65
   385.3 1892.61   395.7 1890.02   403.7 1890.87   411.7 1893.54   419.8 1893.49
   451.9 1910.15     488 1931.93   496.1 1933.84   516.1 1933.08   520.2 1935.37
   528.2 1943.12   532.2  1945.1   548.8 1951.62   564.3  1955.5   578.3 1961.37
#Mann= 5 ,-1,0
       0      .1       0   291.3    .045       0  309.07      .1       0
  386.19     .06       0  486.19      .1       0
#XS Ineff= 2 , 0
                          343.39          1898.6
Permanent Ineff=
       F       F
Bank Sta=291.3,309.07
XS Rating Curve= 0 ,0
Exp/Cntr(USF)=0,0
Exp/Cntr=0.3,0.1

Type RM Length L Ch R = 1 ,1368    ,208.3,208.5,205.4
XS GIS Cut Line= 3
2232294.21433781688244.0510807822232292.23869993688622.385735575
2232362.37384481688894.035944631
#Sta/Elev= 30
       0 1921.37    81.1 1908.79    89.1 1905.76   101.1 1907.07   157.1 1898.33
   205.1 1892.72   261.1 1887.65   280.6 1884.65  289.05 1881.96   301.6 1881.53
  306.741881.961   313.1 1883.86   345.1  1884.1   377.1 1886.03   430.8 1886.61
   443.2 1885.58   472.1 1886.59   480.4 1890.57     501 1904.44   525.1  1914.7
   534.1 1920.44   538.2 1921.31   546.5  1919.9   571.3 1920.21   575.4 1922.39
   583.7 1929.88   620.8 1943.73   633.2 1947.11   641.5 1951.29   658.9 1957.25
#Mann= 5 ,-1,0
       0      .1       0  289.05    .045       0  306.74      .1       0
  558.34     .06       0  658.34      .1       0
Bank Sta=289.05,306.74
XS Rating Curve= 0 ,0
Exp/Cntr(USF)=0,0
Exp/Cntr=0.3,0.1

Type RM Length L Ch R = 1 ,1159    ,355.9,355.3,352.5
XS GIS Cut Line= 4
2232111.40245696688184.8858494152232081.66236715688374.478921996
2232129.30604612688703.3225933672232281.33202336688911.404219404
#Sta/Elev= 30
       0 1917.14      61 1906.44   113.7 1899.09   129.9 1894.96   150.1 1891.97
   267.4 1882.23   303.8    1881     315 1876.32   319.9 1875.46  331.28 1876.33
   352.3 1878.16     373 1882.13   415.4 1878.83   461.4 1878.48   473.5 1882.35
   481.6 1881.16   496.6 1886.56     522 1890.07     539 1889.61     576 1897.17
   590.9  1902.1   635.5 1903.79   640.4 1904.72   656.4 1912.31   670.1 1915.26
   680.1 1922.38   694.9 1923.07   724.6 1932.96   754.4 1947.85   781.9 1956.26
#Mann= 5 ,-1,0
       0      .1       0     315    .045       0  331.28      .1       0
  521.91     .06       0  764.19      .1       0
Bank Sta=315,331.28
XS Rating Curve= 0 ,0
Exp/Cntr(USF)=0,0
Exp/Cntr=0.3,0.1

Type RM Length L Ch R = 1 ,804     ,360.6,367.6,364.2
XS GIS Cut Line= 4
2231750.77793971688208.8851547542231734.04913919688467.252185036
  2231845.574476688801.8281954752232089.07146137689054.618958917
#Sta/Elev= 30
       0 1905.52    92.5 1894.09   184.7 1886.14   196.7 1883.66   212.7 1873.33
   224.8 1871.06   240.8 1870.35   256.8 1871.97   307.3 1871.58     320 1870.33
   357.9 1869.78   391.6 1870.18  413.711866.942   425.4 1866.47  432.541866.943
   442.2 1868.99   467.7 1868.47   480.3 1871.14   543.6 1871.54   556.2 1876.06
   568.7 1878.23     644  1880.9   714.8 1889.52   731.8  1894.4   765.2 1894.17
     777 1899.14   833.6 1909.52   882.8 1921.22     905 1927.11   962.6  1945.2
#Mann= 5 ,-1,0
       0      .1       0  413.71    .045       0  432.54      .1       0
  608.91     .06       0  751.58      .1       0
Bank Sta=413.71,432.54
XS Rating Curve= 0 ,0
Exp/Cntr(USF)=0,0
Exp/Cntr=0.3,0.1

Type RM Length L Ch R = 1 ,436     ,,,
XS GIS Cut Line= 4
2231598.22685839688210.2894896072231439.02275744688648.016531122
2231547.26753818688956.073981483 2231835.8438114689230.985217999
#Sta/Elev= 30
       0 1895.25    66.3  1886.8   147.8 1879.19   203.1 1871.62   228.7 1870.23
     266 1864.47   306.6 1866.01   415.8 1865.06   462.7 1863.13   594.2 1864.27
   602.5 1864.05  613.44 1859.43   618.2 1858.54   643.3 1859.43   655.8 1861.86
   683.2 1863.22   700.2  1865.6   738.4 1865.96   746.8 1867.34   772.3 1868.17
   793.6 1870.97   804.6 1869.46   815.7 1872.58   887.5 1876.77   950.5  1882.1
    1009 1890.78    1037 1892.43  1049.1 1894.84  1080.8 1897.34  1190.9  1910.5
#Mann= 5 ,-1,0
       0      .1       0  613.44    .045       0   643.3      .1       0
   992.3     .06       0  1132.3      .1       0
Bank Sta=613.44,643.3
XS Rating Curve= 0 ,0
Exp/Cntr(USF)=0,0
Exp/Cntr=0.3,0.1
LCMann Table=0

Chan Stop Cuts=-1
Use User Specified Reach Order=0
Composite Channel Slope=5